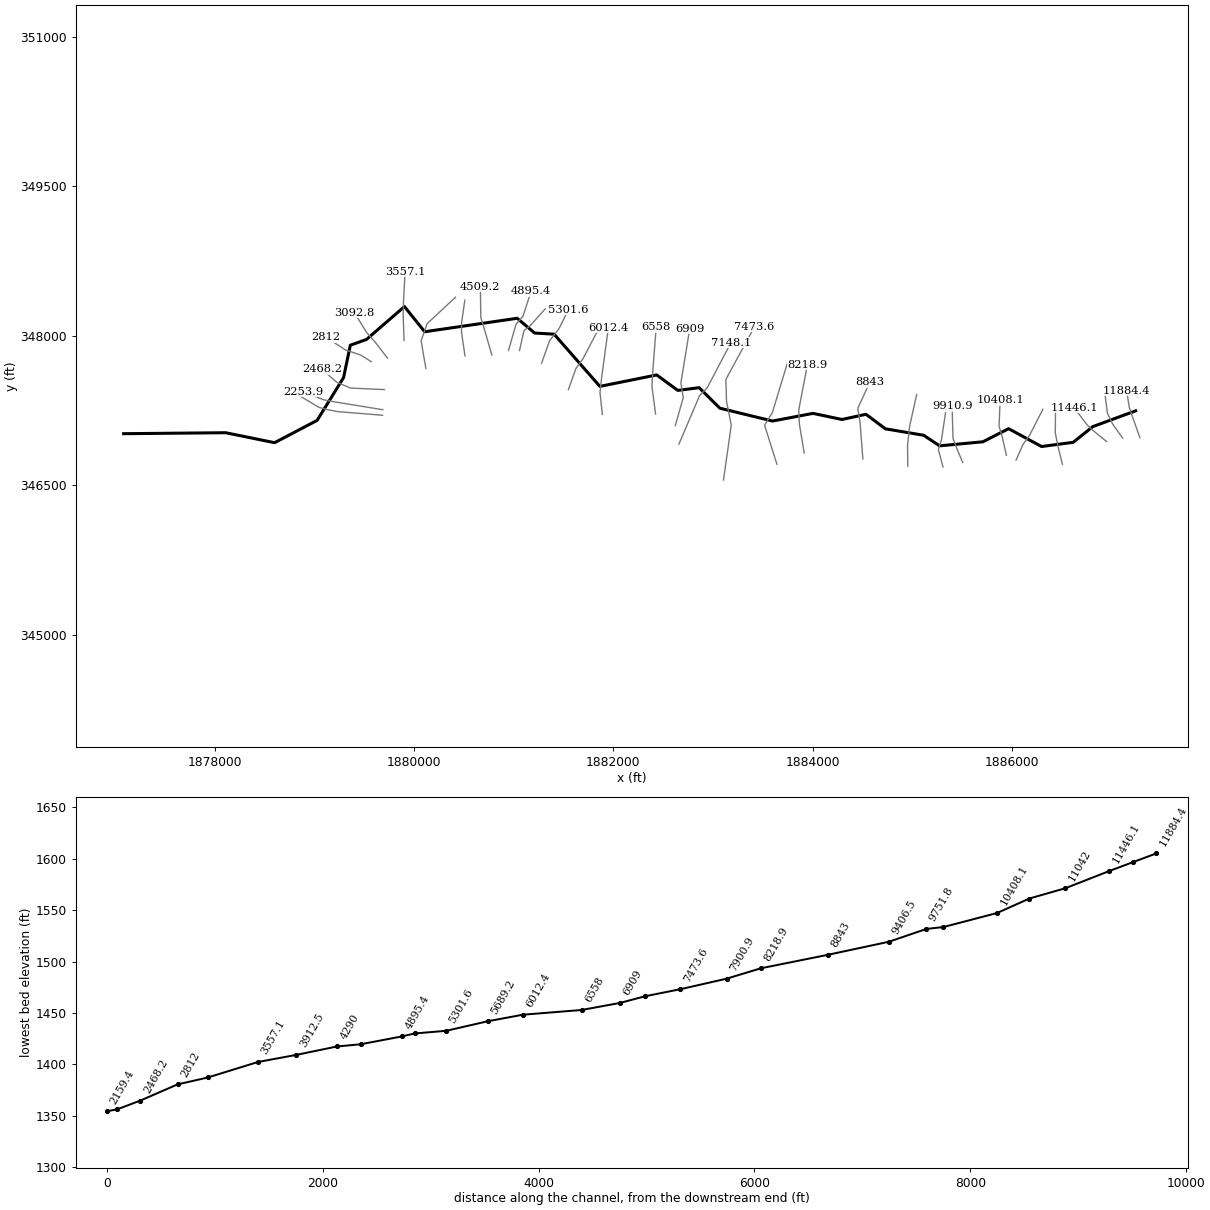
--- THREEFRKCK.prj (project) ---

Proj Title=THREEFRKCK
Current Plan=p01
Default Exp/Contr=0,0
English Units
Geom File=g01
Flow File=f01
Plan File=p01
BEGIN DESCRIPTION:
END DESCRIPTION:
DSS Export Rating Curves= 0
DSS Export Rating Curve Sorted= 0
DSS Export Volume Flow Curves= 0
DXF OffsetX= 0
DXF OffsetY= 0
DXF ScaleX= 0
DXF ScaleY= 0

--- THREEFRKCK.p01 (plan) ---

Plan Title=Floodplain
Program Version=4.00
Geom File=g01
Flow File=f01
K Sum by GR=0
Std Step Tol=0.01
Critical Tol=0.01
Num of Std Step Trials=20
Max Error Tol=0.3
Flow Tol Ratio=0.001
Split Flow NTrial=30
Split Flow Tol=0.02
Split Flow Ratio=0.02
Log Output Level=0
Friction Slope Method=1
Unsteady Friction Slope Method=2
Unsteady Bridges Friction Slope Method=1
Global Log Level=0
CheckData=False
Run HTab=0
Run UNet=0
Run PostProcess=0
UNET Theta=0
UNET Theta Warmup=0
UNET ZTol=0
UNET ZSATol=0
UNET MxIter=0
UNET MaxInSteps=0
UNET DtIC=0
UNET DtMin=0
UNET MaxCRTS=0
UNET WFStab=0
UNET SFStab=0
UNET WFX=0
UNET SFX=0
UNET DSS MLevel=0
UNET DZMax Abort=0
UNET Convert EG Bridges=0
UNET Use Existing IB Tables=0
UNET Froude Limit=0
UNET Froude Power=0
Write IC File=0
Echo Input=False
Echo Output=False
Write Detailed=0

--- THREEFRKCK.f01 (steady flow) ---

Flow Title=NFF Regression Equation
Program Version=4.00
Number of Profiles=1
Profile Names=P100yr
River Rch & RM=THREEFRKCK,Main      ,11884.4
542.9108
River Rch & RM=THREEFRKCK,Main      ,10408.1
563.4434
River Rch & RM=THREEFRKCK,Main      ,7148.1
615.5604
River Rch & RM=THREEFRKCK,Main      ,6558
852.9775
River Rch & RM=THREEFRKCK,Main      ,2049.3
921.3102
River Rch & RM=THREEFRKCK,Main      ,1898.2
2101.788
River Rch & RM=THREEFRKCK,Main      ,378.8
2112.526
Boundary for River Rch & Prof#=THREEFRKCK,Main      ,1
Up Type=0
Dn Type=3
Dn Slope=0.01231

--- THREEFRKCK.g01 (geometry) ---

Geom Title=USGS 10m DEM
Program Version=4.10

River Reach=THREEFRKCK      ,Main
Reach XY= 30
     1887241.496      347246.277     1886811.896      347088.031
     1886615.281      346930.479     1886297.867      346888.369
     1885966.844      347067.197     1885709.031      346935.687
     1885274.135      346895.322     1885115.546      347001.128
     1884731.166      347065.895     1884535.854      347211.729
     1884294.969      347159.645     1884004.604      347220.843
     1883598.354       347144.02     1883069.708      347272.927
     1882862.677      347478.656     1882647.838      347451.312
     1882436.379      347606.432     1881866.583      347491.677
     1881406.928      348015.642     1881211.635      348026.833
     1881036.691      348174.898     1880108.771      348039.854
     1879905.646      348292.458     1879525.437      347963.031
     1879362.472      347904.345     1879294.969      347580.218
     1879029.622      347150.594       1878602.9      346926.726
     1878111.375      347026.833     1877088.371      347017.024

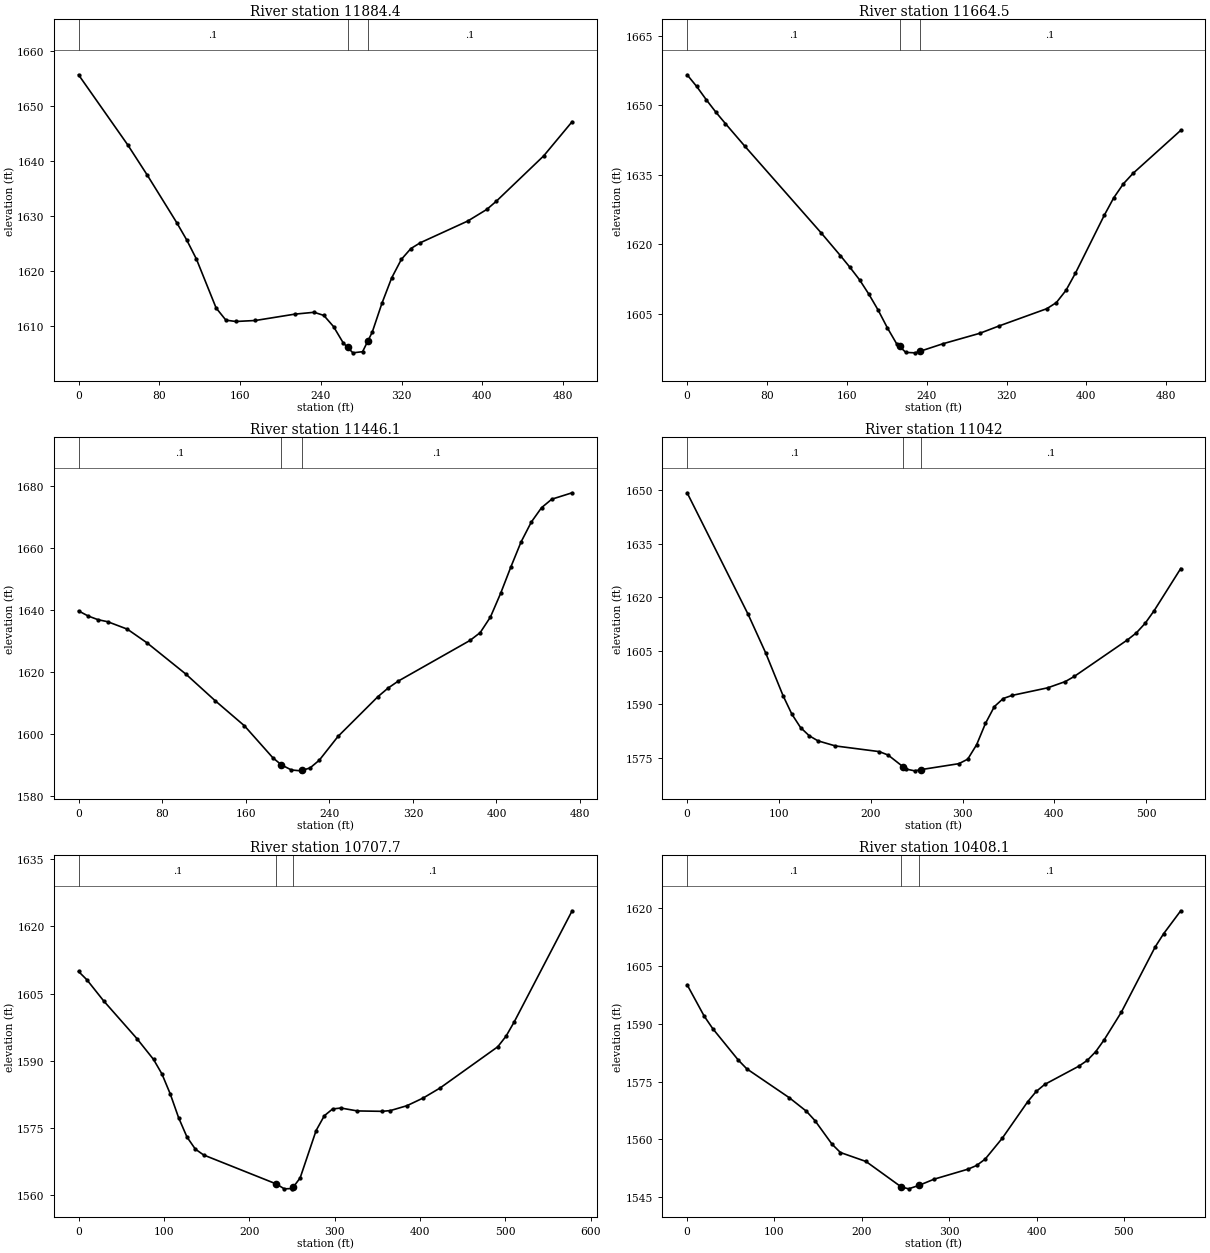
Type RM Length L Ch R = 1 ,11884.4 ,216.9,219.8,222.5
XS GIS Cut Line= 4
     1887284.096      346977.715     1887212.482      347179.538
     1887177.759      347279.365     1887151.718      347446.465
#Sta/Elev= 30
       0 1655.65    48.7 1642.94    68.1 1637.44    97.3 1628.81   107.1  1625.7
   116.8  1622.2   136.3 1613.33     146 1611.12   155.8 1610.88   175.2 1611.06
   214.2 1612.21   233.4 1612.55     243 1611.98   252.6 1609.96   262.2    1607
   266.5 1606.19   271.8 1605.19   281.4  1605.4   286.5 1607.29     291 1608.96
   300.6  1614.2   310.2 1618.78   319.8 1622.15   329.2 1624.11   338.6 1625.17
   385.6 1629.11   404.4 1631.21   413.8 1632.69   460.8 1640.93     489 1647.14
#Mann= 3 , 0 , 0
       0      .1       0   266.5    .045       0   286.5      .1       0
Bank Sta=266.5,286.5
XS Rating Curve= 0 ,0
Exp/Cntr=0.3,0.1

Type RM Length L Ch R = 1 ,11664.5 ,209,218.4,227.7
XS GIS Cut Line= 4
     1887110.485      346973.375     1887010.659      347114.434
     1886958.575      347222.941     1886932.534      347422.594
#Sta/Elev= 30
       0 1656.63     9.6  1654.1    19.2 1651.24    28.8 1648.56    38.4 1646.08
    57.6 1641.26   134.4 1622.46   153.6 1617.57   163.2 1615.03   172.8 1612.34
   182.1 1609.24   191.3 1605.84   200.6 1601.99   209.8 1598.58   212.8 1597.97
   219.1 1596.68   228.4 1596.59   232.8 1596.89   256.1 1598.54   293.2 1600.81
   312.3 1602.38   360.3 1606.12   369.9 1607.44   379.5 1610.07     389 1613.79
   417.8 1626.25   427.4 1630.07     437 1633.08   446.6 1635.32   494.5 1644.63
#Mann= 3 , 0 , 0
       0      .1       0   212.8    .045       0   232.8      .1       0
Bank Sta=212.8,232.8
XS Rating Curve= 0 ,0
Exp/Cntr=0.3,0.1

Type RM Length L Ch R = 1 ,11446.1 ,419.1,404.1,387.8
XS GIS Cut Line= 4
     1886949.895      346938.653     1886819.686       347044.99
     1886754.582      347105.754     1886624.374      347277.195
#Sta/Elev= 30
       0 1639.57     9.3 1637.91    18.7 1636.73      28 1636.07    46.7 1633.68
    65.4  1629.3   102.7 1619.19   130.8 1610.59   158.8  1602.5   185.9 1592.22
   194.1 1589.92   203.7 1588.26   212.6 1587.98   214.1 1588.14   221.6 1588.92
   230.4 1591.41   248.3 1599.07   286.5  1611.9   296.3 1614.69   306.1 1616.95
   374.6 1630.03   384.4 1632.56   394.2 1637.59     404 1645.26   413.7  1653.7
   423.5  1661.8   433.3 1668.21   443.1 1672.86   452.9  1675.6   472.4 1677.67
#Mann= 3 , 0 , 0
       0      .1       0   194.1    .045       0   214.1      .1       0
Bank Sta=194.1,214.1
XS Rating Curve= 0 ,0
Exp/Cntr=0.3,0.1

Type RM Length L Ch R = 1 ,11042   ,355.7,334.3,313.2
XS GIS Cut Line= 4
     1886507.186      346708.618     1886461.614       346893.08
     1886435.572      347025.458     1886437.742      347238.132
#Sta/Elev= 30
       0 1649.31    66.5 1615.19    85.5 1604.44   104.5 1592.42     114 1587.28
   123.5  1583.5     133 1581.18   142.5 1579.76   161.5 1578.33   209.3 1576.74
   218.9 1575.78   234.9 1572.55   238.2 1571.86   247.8 1571.35   254.9  1571.7
     296 1573.36   305.6 1574.62   315.3 1578.67   324.9 1584.63   334.6 1589.36
   344.3 1591.63   353.9  1592.5   392.6 1594.62   411.9 1596.38   421.6 1597.81
   479.6 1608.07   489.3 1610.04   498.9 1612.73   508.6 1616.24   537.6 1628.08
#Mann= 3 , 0 , 0
       0      .1       0   234.9    .045       0   254.9      .1       0
Bank Sta=234.9,254.9
XS Rating Curve= 0 ,0
Exp/Cntr=0.3,0.1

Type RM Length L Ch R = 1 ,10707.7 ,276.2,299.6,323.1
XS GIS Cut Line= 4
     1886041.909      346752.021     1886113.523      346912.611
     1886174.287      346995.077     1886311.006      347262.004
#Sta/Elev= 30
       0 1609.93     9.8 1608.07    29.3 1603.38    68.4 1594.91    87.9 1590.24
    97.7    1587   107.4 1582.55   117.2 1577.23     127  1572.9   136.8 1570.19
   146.5 1568.88   231.8 1562.38     241  1561.3   250.3 1561.36   251.8 1561.75
   259.6 1563.75   278.3 1574.35   287.9 1577.65   297.6 1579.17   307.3 1579.38
   326.6 1578.73   355.7 1578.64   365.3 1578.81   384.7  1579.9     404 1581.65
   423.4 1583.85   491.1 1593.09   500.8 1595.46   510.4 1598.67   578.2 1623.51
#Mann= 3 , 0 , 0
       0      .1       0   231.8    .045       0   251.8      .1       0
Bank Sta=231.8,251.8
XS Rating Curve= 0 ,0
Exp/Cntr=0.3,0.1

Type RM Length L Ch R = 1 ,10408.1 ,495.5,497.2,498.7
XS GIS Cut Line= 4
      1885945.12      346799.764     1885899.548      346999.417
     1885871.336      347092.733     1885882.186       347355.32
#Sta/Elev= 30
       0 1600.12    19.5    1592    29.3 1588.75    58.5 1580.61    68.3 1578.32
     117 1570.82   136.5 1567.33   146.3 1564.91   165.8  1558.8   175.5 1556.62
   204.8 1554.29   245.1  1547.7   253.5  1547.2   265.1 1548.07   282.8 1549.71
   321.7 1552.31   331.5 1553.27   341.2 1554.91   360.7  1560.3   389.9 1569.79
   399.6 1572.44   409.4 1574.28   448.3 1578.99     458 1580.49   467.8 1582.78
   477.5 1585.86     497 1592.96   535.9 1609.95   545.6 1613.38   565.1  1619.3
#Mann= 3 , 0 , 0
       0      .1       0   245.1    .045       0   265.1      .1       0
Bank Sta=245.1,265.1
XS Rating Curve= 0 ,0
Exp/Cntr=0.3,0.1

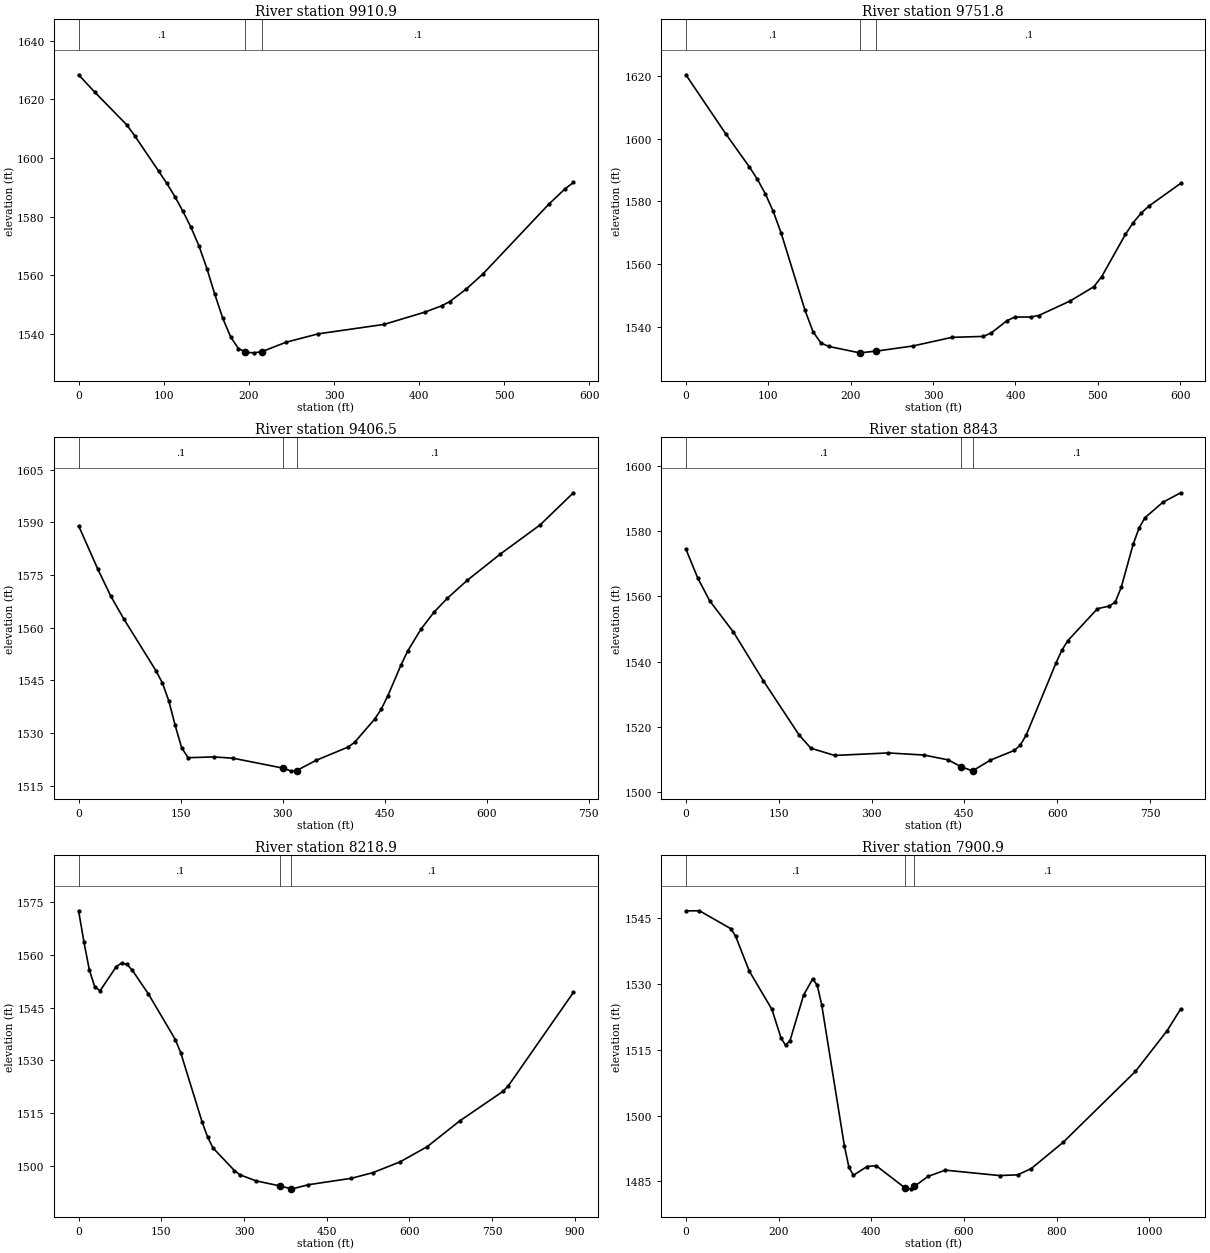
Type RM Length L Ch R = 1 ,9910.9  ,176.3,159.1,141.9
XS GIS Cut Line= 4
     1885506.752      346728.149     1885448.159      346867.038
     1885409.096      346971.205     1885400.416      347290.215
#Sta/Elev= 30
       0 1628.34    18.8 1622.48    56.5 1611.29      66 1607.51    94.2 1595.41
   103.6 1591.33   113.1 1586.82   122.5 1581.83   131.9  1576.4   141.3 1570.06
   150.7 1562.29     160 1553.49   169.3 1545.38   178.6 1538.95   187.8 1535.01
   195.5 1533.93   197.1 1533.71   206.4 1533.55   215.5 1533.98   243.4 1537.14
   281.3 1540.02   358.7 1543.24     407 1547.46   426.4 1549.58   436.1 1551.05
   455.4 1555.32   474.8 1560.42   552.1 1584.18   571.4 1589.48   581.1 1591.62
#Mann= 3 , 0 , 0
       0      .1       0   195.5    .045       0   215.5      .1       0
Bank Sta=195.5,215.5
XS Rating Curve= 0 ,0
Exp/Cntr=0.3,0.1

Type RM Length L Ch R = 1 ,9751.8  ,340.2,345.3,350.4
XS GIS Cut Line= 4
     1885309.255      346682.005      1885262.38      346859.088
      1885293.63      346955.443     1885340.505      347267.943
#Sta/Elev= 30
       0 1620.45    48.2 1601.66    77.1 1591.02    86.8 1587.07    96.4 1582.46
     106 1576.84   115.7 1569.84   144.6 1545.24   154.3 1538.42   163.9 1534.81
   173.5 1533.72   210.8 1531.68   211.3 1531.69   231.3 1532.24   275.3 1533.86
   322.8 1536.62   361.1 1536.93   370.7 1538.05   389.8 1541.98   399.4  1543.1
   418.5 1543.12   428.1 1543.59   466.4 1548.24   495.1 1552.79   504.7 1556.03
   533.4 1569.48     543 1573.28   552.6  1576.3   562.2 1578.59   600.5 1585.78
#Mann= 3 , 0 , 0
       0      .1       0   211.3    .045       0   231.3      .1       0
Bank Sta=211.3,231.3
XS Rating Curve= 0 ,0
Exp/Cntr=0.3,0.1

Type RM Length L Ch R = 1 ,9406.5  ,557.1,563.5,569.9
XS GIS Cut Line= 4
     1884955.537      346691.257     1884953.367       346899.59
     1884972.898      347086.222     1885044.513      347409.573
#Sta/Elev= 30
       0 1589.03    28.4 1576.62    47.4 1568.96    66.3 1562.55   113.6  1547.8
   123.1 1544.31   132.6 1539.18     142 1532.17   151.5 1525.81     161    1523
   198.9 1523.22   227.1 1522.85   300.3 1520.04   311.6 1519.26   320.3 1519.32
   349.1 1522.25     396 1526.02   405.7 1527.38     435 1533.95   444.7 1536.77
   454.4 1540.58   473.9  1549.4   483.7 1553.37   503.1 1559.56   522.6 1564.48
   542.1 1568.42   571.3 1573.51     620    1581   678.5  1589.3   727.2 1598.42
#Mann= 3 , 0 , 0
       0      .1       0   300.3    .045       0   320.3      .1       0
Bank Sta=300.3,320.3
XS Rating Curve= 0 ,0
Exp/Cntr=0.3,0.1

Type RM Length L Ch R = 1 ,8843    ,626.6,624.1,621.1
XS GIS Cut Line= 4
     1884505.016       346763.74     1884476.616      347127.947
     1884454.481      347272.478     1884574.461      347534.139
#Sta/Elev= 30
       0 1574.43    19.2 1565.56    38.4 1558.62    76.9 1549.02     125 1534.19
   182.7 1517.61   201.9 1513.51   240.3  1511.3   326.9 1512.07   384.8 1511.42
   423.8 1509.94   444.2 1507.88   462.8 1506.59   464.2 1506.69     492 1509.87
   530.7 1512.84   540.3 1514.48   549.9 1517.56   597.9 1539.55   607.5 1543.52
   617.1 1546.43     665  1556.2   684.2 1557.01   693.8 1558.26   703.4 1562.76
   722.6  1575.9   732.2 1580.88   741.8 1584.05   770.6 1588.75   799.4 1591.66
#Mann= 3 , 0 , 0
       0      .1       0   444.2    .045       0   464.2      .1       0
Bank Sta=444.2,464.2
XS Rating Curve= 0 ,0
Exp/Cntr=0.3,0.1

Type RM Length L Ch R = 1 ,8218.9  ,333.1,318.1,302.9
XS GIS Cut Line= 4
     1883916.041      346823.636     1883868.298      347112.264
     1883861.787      347255.493     1883948.593      347709.052
#Sta/Elev= 30
       0 1572.55     9.8 1563.59    19.5  1555.7    29.3 1550.92      39 1549.79
    68.3 1556.64      78 1557.66    87.8 1557.28    97.5 1555.63   126.8 1548.84
   175.5  1535.9   185.3 1532.14   224.3 1512.35     234  1508.2   243.8 1505.06
   282.8  1498.6   292.6 1497.42   321.2 1495.71   365.5 1494.23   385.5 1493.44
   388.1 1493.41   416.8 1494.58   494.9 1496.41   534.2 1498.03   583.3 1501.09
   632.4  1505.4   691.4 1512.73     770 1521.15   779.8 1522.75   897.7  1549.3
#Mann= 3 , 0 , 0
       0      .1       0   365.5    .045       0   385.5      .1       0
Bank Sta=365.5,385.5
XS Rating Curve= 0 ,0
Exp/Cntr=0.3,0.1

Type RM Length L Ch R = 1 ,7900.9  ,408.5,427.3,446.1
XS GIS Cut Line= 4
     1883642.603      346710.788      1883518.97      347102.122
      1883597.03      347229.452       1883744.6      347715.563
#Sta/Elev= 30
       0 1546.68    29.3  1546.7    97.7 1542.57   107.5 1540.84   136.8 1532.94
   185.7  1524.2   205.2 1517.72     215 1516.04   224.7 1517.09   254.1 1527.51
   273.6 1531.14   283.4 1529.75   293.1 1525.25     342 1493.11   351.8 1488.23
   361.5 1486.38   390.9 1488.38   410.4 1488.58   473.2 1483.48   485.1 1483.29
   493.2 1483.85   522.4 1486.12   559.8 1487.55     677 1486.32   716.1 1486.48
   745.4 1487.92   813.8 1493.87   970.1 1510.06  1038.5 1519.35  1067.8  1524.3
#Mann= 3 , 0 , 0
       0      .1       0   473.2    .045       0   493.2      .1       0
Bank Sta=473.2,493.2
XS Rating Curve= 0 ,0
Exp/Cntr=0.3,0.1

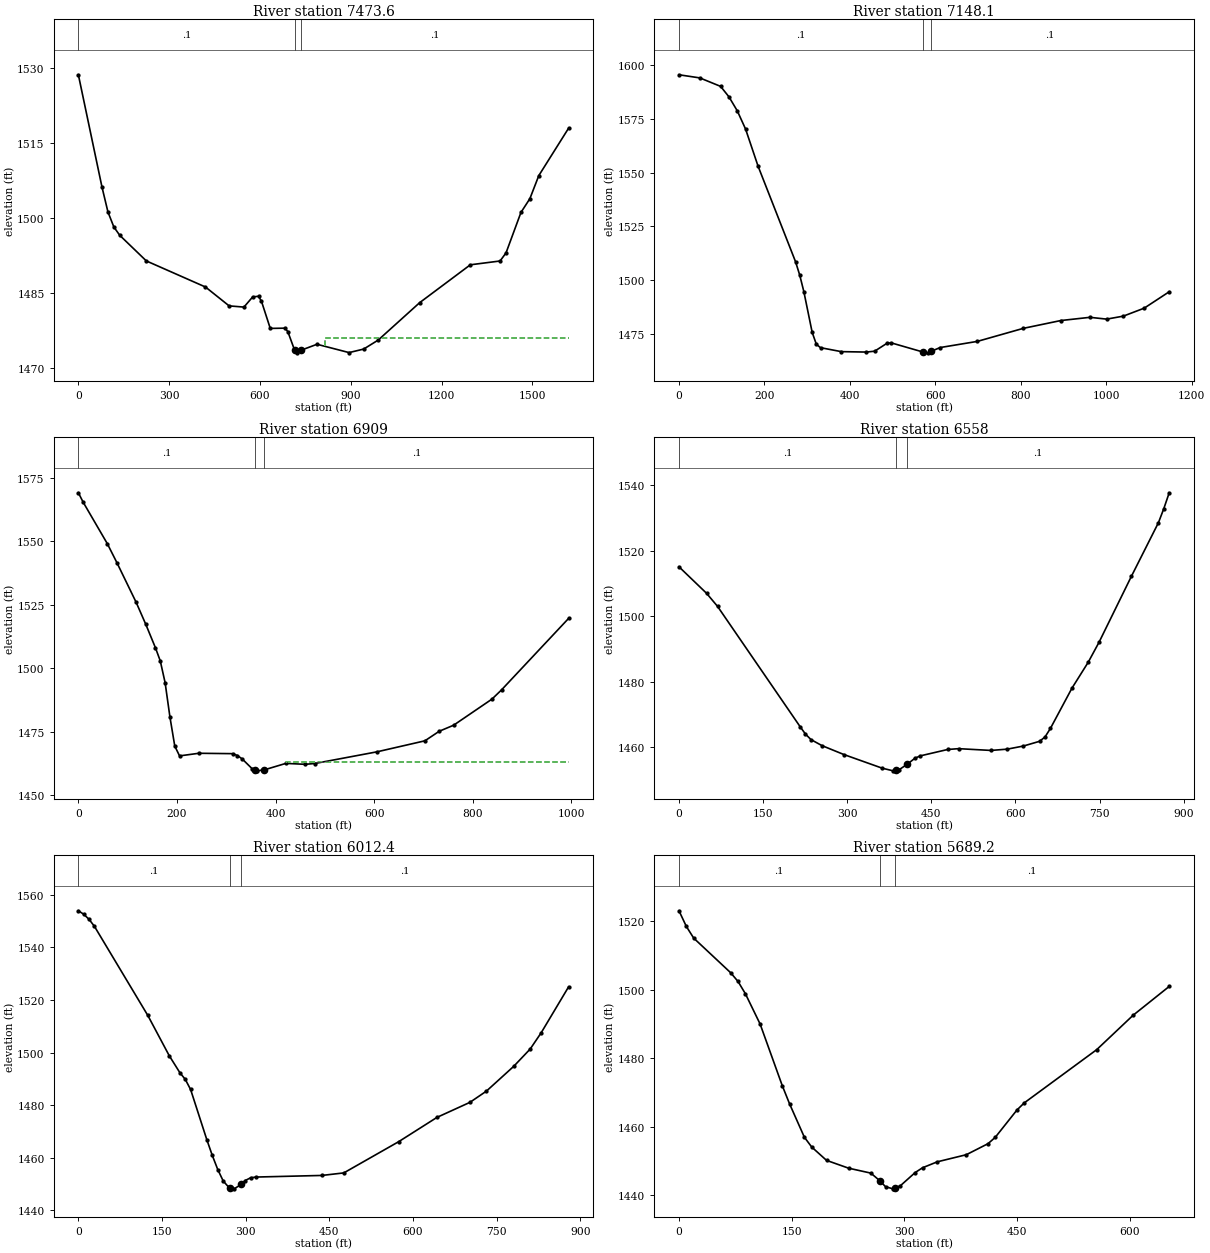
Type RM Length L Ch R = 1 ,7473.6  ,349.4,325.5,301.2
XS GIS Cut Line= 5
     1883106.579      346552.368     1883184.704      347103.583
     1883136.961      347340.129      1883130.45      347561.483
     1883416.909      348088.827
#Sta/Elev= 30
       0 1528.63    78.1 1506.18    97.7 1501.23   117.2 1498.23   136.7 1496.56
   224.6 1491.44     420 1486.23   498.1 1482.46     547 1482.22     576 1484.26
   595.3 1484.38     605 1483.37     634 1477.96   682.2 1478.01   691.9 1477.34
   714.3 1473.63   720.8 1473.08   734.3 1473.57   788.4 1474.79   894.3 1473.13
   942.5 1473.83   990.6 1475.63  1127.7 1483.11    1295 1490.67  1393.3 1491.43
    1413 1493.06  1462.2 1501.13  1491.7 1503.88  1521.2 1508.49  1619.6 1517.96
#Mann= 3 , 0 , 0
       0      .1       0   714.3    .045       0   734.3      .1       0
#XS Ineff= 2 , 0
                          813.51         1475.95
Permanent Ineff=
       F       F
Bank Sta=714.3,734.3
XS Rating Curve= 0 ,0
Exp/Cntr=0.3,0.1

Type RM Length L Ch R = 1 ,7148.1  ,215.9,239.1,262.4
XS GIS Cut Line= 4
      1882659.53      346912.611     1882865.693      347396.552
     1882943.818      347479.017     1883180.364      347928.236
#Sta/Elev= 30
       0 1595.49    48.7 1594.04    97.4  1590.1   116.9 1585.25   136.4 1578.74
   155.9 1570.23   185.1    1553   272.8 1508.59   282.5 1502.43   292.2 1494.72
   311.7 1475.77   321.5 1470.22   331.2 1468.64   379.9  1466.8   438.4  1466.6
   457.8    1467   487.1 1470.72   496.8 1470.87   570.3 1466.66   582.8 1466.24
   590.3 1466.96   611.2  1468.7   698.2 1471.56   805.6 1477.61   893.5 1481.25
   961.8 1482.75  1000.9 1481.91  1039.9  1483.3  1088.7    1487  1147.3 1494.63
#Mann= 3 , 0 , 0
       0      .1       0   570.3    .045       0   590.3      .1       0
#XS Ineff= 2 , 0
          496.34 1470.72
Permanent Ineff=
       F       F
Bank Sta=570.3,590.3
XS Rating Curve= 0 ,0
Exp/Cntr=0.3,0.1

Type RM Length L Ch R = 1 ,6909    ,356.5,351,344.8
XS GIS Cut Line= 4
     1882622.638      347097.073     1882702.933      347379.191
     1882679.061       347524.59     1882768.037      348071.465
#Sta/Elev= 30
       0 1569.02     9.8 1565.29    58.7 1549.01    78.2 1541.52   117.3  1525.9
   136.9 1517.22   156.4 1508.03   166.2 1502.87     176 1494.32   185.8 1480.81
   195.6 1469.37   205.3  1465.5   244.4 1466.53     313 1466.38   322.8 1465.65
   332.6 1464.27   352.3 1460.51   357.5 1460.04   362.1 1459.62   377.5 1460.02
     421 1462.55   460.1 1462.19   479.6  1462.5   605.9  1467.1   703.1 1471.43
   732.3  1475.2   761.4 1477.57   839.2 1487.84   858.6 1491.46   994.7 1519.59
#Mann= 3 , 0 , 0
       0      .1       0   357.5    .045       0   377.5      .1       0
#XS Ineff= 2 , 0
                          421.27         1463.06
Permanent Ineff=
       F       F
Bank Sta=357.5,377.5
XS Rating Curve= 0 ,0
Exp/Cntr=0.3,0.1

Type RM Length L Ch R = 1 ,6558    ,546.7,545.6,544.3
XS GIS Cut Line= 4
     1882425.155      347214.261     1882388.263      347496.379
     1882401.284      347700.372     1882431.666      348084.486
#Sta/Elev= 30
       0 1515.04    49.1 1506.98    68.7 1502.99   215.8 1466.36   225.6 1464.04
   235.5 1462.36   255.1 1460.53   294.2 1457.81   362.4 1453.66   381.9 1452.85
   387.3 1452.98   391.6 1453.08   407.3  1454.9   420.8  1456.7   430.5 1457.42
   479.2 1459.36   498.6 1459.61   556.4 1459.07   585.3 1459.46   614.2 1460.41
     643 1461.85   652.7 1463.17   662.3 1465.76   700.8 1478.06   729.8 1485.96
     749 1492.02   806.8 1512.15     855 1528.49   864.6 1532.78   874.2  1537.6
#Mann= 3 , 0 , 0
       0      .1       0   387.3    .045       0   407.3      .1       0
Bank Sta=387.3,407.3
XS Rating Curve= 0 ,0
Exp/Cntr=0.3,0.1

Type RM Length L Ch R = 1 ,6012.4  ,335.8,323.2,310.4
XS GIS Cut Line= 4
     1881891.301       347209.92      1881867.43      347429.104
     1881884.791      347585.354     1881952.065      348082.316
#Sta/Elev= 30
       0 1553.89     9.6 1552.58    19.2 1550.63    28.8 1547.98   124.6  1514.1
     163 1498.81   182.1 1492.35   191.7 1489.84   201.3 1485.98   230.3 1466.96
   240.1 1460.98     250 1455.57   259.8  1451.2   269.6 1448.86     272 1448.71
   279.4 1448.23     292 1449.91   299.1 1451.38   308.9 1452.43   318.7 1452.71
   436.7 1453.32     476 1454.28   574.4 1466.14   643.2 1475.39   702.2 1481.09
   731.7 1485.34   780.8 1494.78   810.4 1501.38     830 1507.52   879.2 1524.98
#Mann= 3 , 0 , 0
       0      .1       0     272    .045       0     292      .1       0
Bank Sta=272,292
XS Rating Curve= 0 ,0
Exp/Cntr=0.3,0.1

Type RM Length L Ch R = 1 ,5689.2  ,388.7,387.5,386.3
XS GIS Cut Line= 4
     1881550.589      347459.486     1881626.544       347672.16
     1881695.989      347767.646     1881839.218      348041.083
#Sta/Elev= 30
       0 1523.06     9.8 1518.49    19.6 1515.08    68.7    1505    78.6 1502.43
    88.4 1498.85     108 1490.01   137.5 1472.02   147.3 1466.67   166.9 1456.98
   176.7 1454.11   196.4 1450.22   225.8 1447.94   255.4  1446.5     267 1444.34
     275 1442.53   284.9 1441.91     287  1442.1   294.7 1442.81   314.4 1446.66
   324.2 1448.06   343.9  1449.8   382.5 1451.87   411.4 1455.09   421.1 1456.96
     450 1464.94   459.6 1466.99   556.1 1482.53   604.4 1492.54   652.6 1500.98
#Mann= 3 , 0 , 0
       0      .1       0     267    .045       0     287      .1       0
Bank Sta=267,287
XS Rating Curve= 0 ,0
Exp/Cntr=0.3,0.1

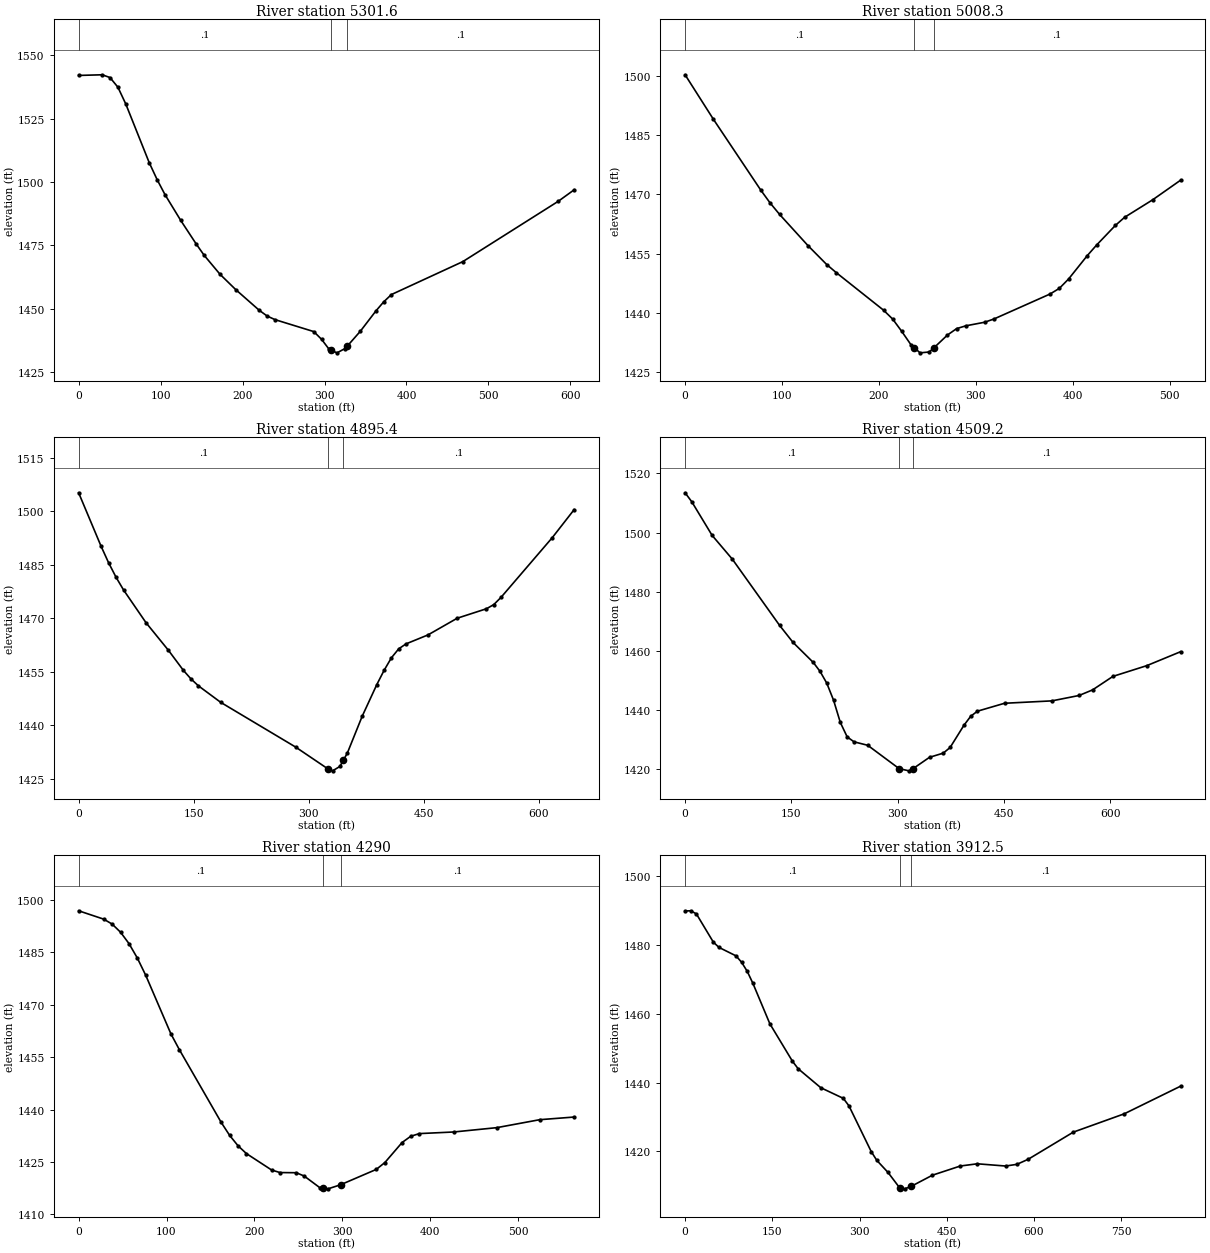
Type RM Length L Ch R = 1 ,5301.6  ,299,293.3,287.6
XS GIS Cut Line= 4
     1881281.492      347724.243     1881361.787      347949.938
     1881455.103      348069.295     1881550.589      348260.267
#Sta/Elev= 30
       0  1542.1    28.8 1542.36    38.3 1541.26    47.9 1537.46    57.5 1530.85
    86.2  1507.6    95.8 1500.94   105.4 1495.02   124.6 1484.84   143.7 1475.43
   153.3 1471.02   172.5 1463.59   191.6 1457.56   220.4 1449.36     230  1447.1
   239.6 1445.68   286.9 1440.96   296.4 1437.91   305.8 1433.89     308 1433.58
   315.3 1432.57   324.8 1434.24     328 1435.31   343.7 1441.09   362.6 1449.07
   372.1 1452.66   381.6 1455.58   468.7 1468.58   585.2 1492.41   604.6 1496.95
#Mann= 3 , 0 , 0
       0      .1       0     308    .045       0     328      .1       0
Bank Sta=308,328
XS Rating Curve= 0 ,0
Exp/Cntr=0.3,0.1

Type RM Length L Ch R = 1 ,5008.3  ,108.3,112.9,117.5
XS GIS Cut Line= 4
      1881059.95      347851.276     1881105.089      348050.929
     1881164.116      348097.804      1881318.63      348269.679
#Sta/Elev= 30
       0  1500.2    29.2 1488.96      78 1471.09    87.7 1467.82    97.5 1464.92
   126.7 1457.06   146.2 1452.24     156 1450.21   204.7 1440.74   214.1  1438.5
   223.5 1435.38     233    1432   236.4 1431.26   242.4 1429.96   251.8 1430.17
   256.4 1431.16   270.6 1434.45   280.1 1436.08   289.7 1436.79     309 1437.69
   318.6 1438.51   376.4 1444.81     386 1446.23   395.6 1448.61   414.9 1454.52
   424.5 1457.19   443.8 1462.13   453.4  1464.2   482.3 1468.61   511.2 1473.58
#Mann= 3 , 0 , 0
       0      .1       0   236.4    .045       0   256.4      .1       0
Bank Sta=236.4,256.4
XS Rating Curve= 0 ,0
Exp/Cntr=0.3,0.1

Type RM Length L Ch R = 1 ,4895.4  ,360.7,386.2,411.4
XS GIS Cut Line= 4
     1880949.461      347852.281     1881025.416      348114.868
      1881094.86      348195.163     1881177.325       348449.07
#Sta/Elev= 30
       0 1505.17    29.3 1490.17      39 1485.59    48.8 1481.49    58.6 1477.92
    87.9 1468.74   117.2 1460.98   136.7 1455.36   146.4 1453.01   156.2 1451.04
   185.5 1446.38     283 1433.87   325.5  1427.7   331.3 1427.19   340.9 1428.43
   345.5 1430.21   350.6 1432.19   369.9 1442.48     389 1451.37   398.6 1455.41
   408.1  1458.9   417.6 1461.41   427.2  1462.8   455.8 1465.31   493.9 1469.99
   532.1 1472.65   541.6 1473.81   551.1 1475.85   617.9 1492.58   646.5 1500.46
#Mann= 3 , 0 , 0
       0      .1       0   325.5    .045       0   345.5      .1       0
Bank Sta=325.5,345.5
XS Rating Curve= 0 ,0
Exp/Cntr=0.3,0.1

Type RM Length L Ch R = 1 ,4509.2  ,226.5,219.3,212
XS GIS Cut Line= 4
      1880782.36      347806.708     1880721.596      348017.212
     1880671.683      348184.313     1880667.343      348490.302
#Sta/Elev= 30
       0 1513.43     9.5 1510.37    38.1 1499.05    66.7 1490.99   133.4 1468.62
   152.4 1462.86     181 1456.09   190.5 1453.08     200  1449.1   209.6 1443.32
   219.1 1435.84   228.8 1430.94   238.5 1429.28   257.8 1428.11   302.1 1420.23
     316 1419.48   322.1 1420.27     345 1424.05   364.4 1425.46   374.1 1427.37
   393.5 1434.83   403.1  1437.9   412.6 1439.63   450.9 1442.31   517.8 1443.12
   556.1 1444.94   575.2 1446.83   603.9 1451.39   651.7 1455.02   699.5 1459.74
#Mann= 3 , 0 , 0
       0      .1       0   302.1    .045       0   322.1      .1       0
Bank Sta=302.1,322.1
XS Rating Curve= 0 ,0
Exp/Cntr=0.3,0.1

Type RM Length L Ch R = 1 ,4290    ,386.2,377.5,368.8
XS GIS Cut Line= 4
     1880513.075      347797.456     1880478.353      348033.568
     1880478.353      348123.845     1880511.339      348356.484
#Sta/Elev= 30
       0  1496.9    28.6  1494.5    38.2 1493.08    47.7 1490.76    57.3 1487.51
    66.8 1483.37    76.4 1478.41     105 1461.68   114.6 1457.16   162.3 1436.31
   171.8 1432.63   181.4 1429.64   190.9 1427.42   219.6 1422.71   229.1 1421.98
   247.7 1421.93   256.7 1420.98   274.8 1417.59     278 1417.49   283.8 1417.32
     298 1418.48   338.7 1422.88   348.5 1424.85   368.1 1430.58   377.9 1432.36
   387.7 1433.13   426.8 1433.59   475.8 1434.83   524.7 1437.11   563.9 1437.87
#Mann= 3 , 0 , 0
       0      .1       0     278    .045       0     298      .1       0
Bank Sta=278,298
XS Rating Curve= 0 ,0
Exp/Cntr=0.3,0.1

Type RM Length L Ch R = 1 ,3912.5  ,346.9,355.4,363.3
XS GIS Cut Line= 4
     1880120.468       347672.16     1880072.725      347949.938
     1880133.489      348121.379     1880417.777      348386.136
#Sta/Elev= 30
       0 1489.91     9.7 1489.97    19.4 1489.07    48.6 1480.85    58.3 1479.32
    87.5 1476.87    97.2    1475   106.9 1472.35   116.6 1468.88   145.8 1457.11
   184.7 1446.21   194.4 1444.06   233.3 1438.54   272.1 1435.44   281.8 1433.26
   320.1 1419.96   329.7 1417.42   348.9 1413.92   369.1 1409.41   377.6 1409.14
   389.1 1409.89   425.4 1413.11   473.4 1415.78   502.6 1416.42   551.2 1415.77
   570.6 1416.26     590 1417.73   667.7 1425.63   755.1 1430.94   852.2 1438.99
#Mann= 3 , 0 , 0
       0      .1       0   369.1    .045       0   389.1      .1       0
Bank Sta=369.1,389.1
XS Rating Curve= 0 ,0
Exp/Cntr=0.3,0.1

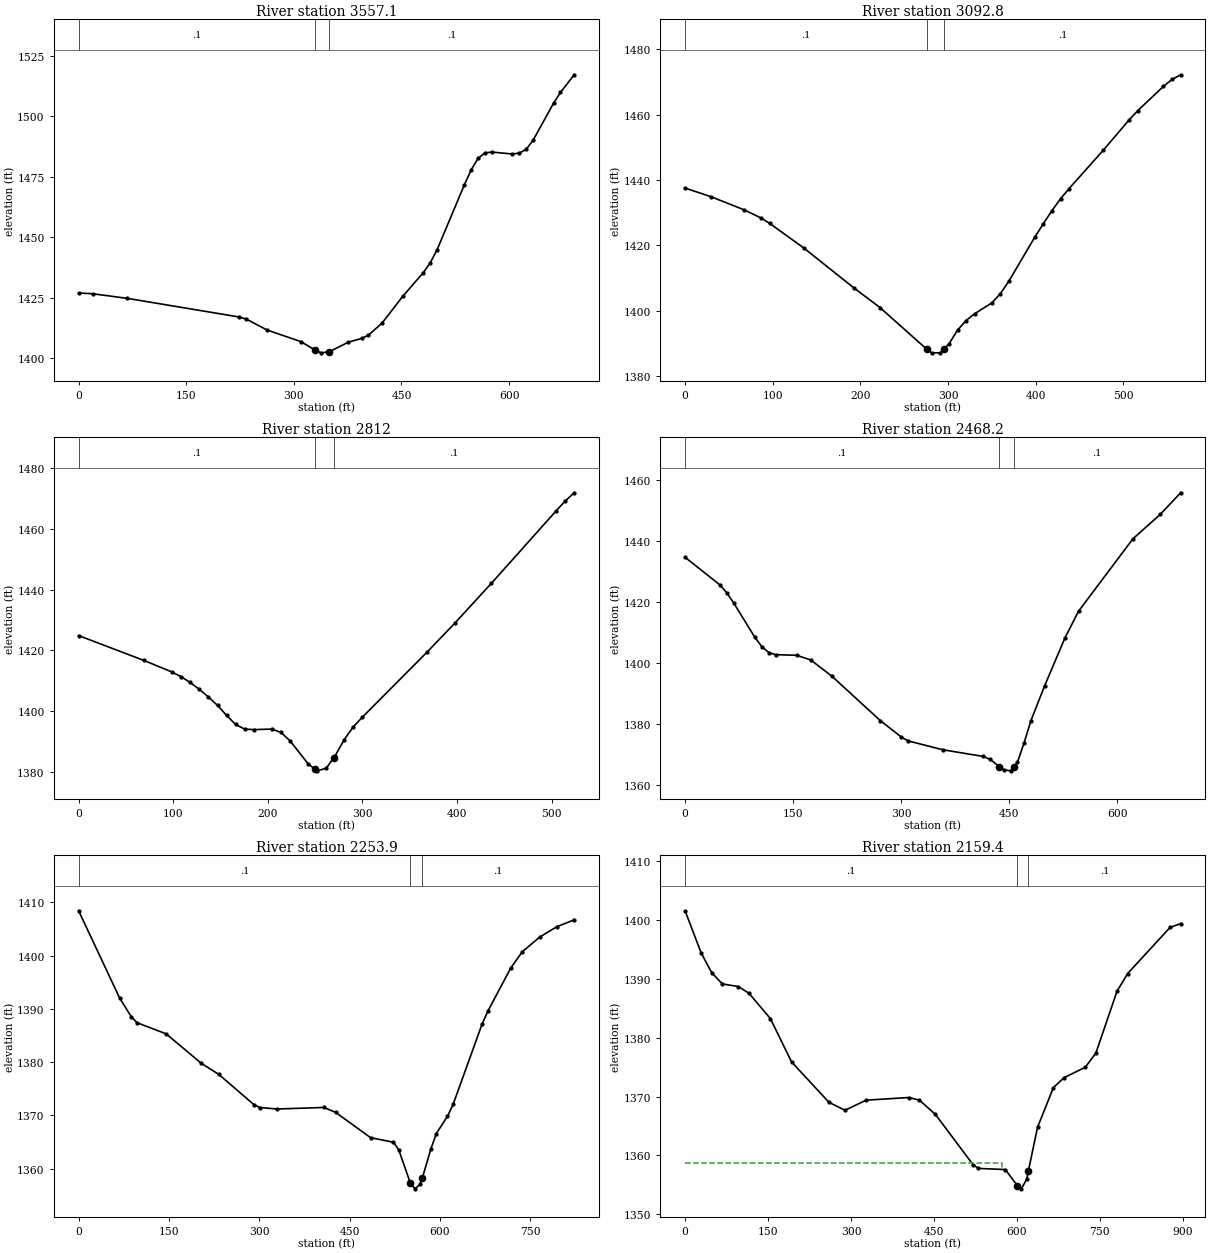
Type RM Length L Ch R = 1 ,3557.1  ,444.9,464.3,483.2
XS GIS Cut Line= 4
     1879901.284      347952.108     1879892.603      348214.695
     1879896.943      348355.754     1879912.134      348642.212
#Sta/Elev= 30
       0 1426.94    19.5 1426.64    68.1 1424.72   223.8 1417.03   233.5  1416.2
   262.7 1411.65   309.8 1406.86   329.2 1403.42     338 1402.22   349.2 1402.65
   375.6 1406.57   394.4 1408.17   403.9 1409.52     423 1414.54   451.7 1425.54
   480.4 1435.36   489.9 1439.33   499.5 1444.72   537.7 1471.69   547.3 1477.94
   556.8 1482.58   566.4 1484.87     576 1485.18   604.7 1484.38   614.2 1484.74
   623.8 1486.32   633.3 1489.98     662 1505.41   671.6 1509.81   690.7 1517.12
#Mann= 3 , 0 , 0
       0      .1       0   329.2    .045       0   349.2      .1       0
Bank Sta=329.2,349.2
XS Rating Curve= 0 ,0
Exp/Cntr=0.3,0.1

Type RM Length L Ch R = 1 ,3092.8  ,267,280.8,294.2
XS GIS Cut Line= 4
     1879736.353      347774.156     1879612.655      347934.747
      1879528.02      348030.233     1879404.322      348229.886
#Sta/Elev= 30
       0 1437.54      29 1434.96    67.6 1430.86    86.9 1428.35    96.5 1426.73
   135.1 1419.28     193 1406.91   222.3    1401   275.4 1388.31   281.2 1387.15
     291 1387.16   295.4 1388.35   300.9 1389.84   310.7 1394.08   320.5 1397.04
   330.3 1399.12   349.9 1402.43   359.7 1405.28   369.4 1409.14   398.8 1422.52
   408.6 1426.65   418.4 1430.65   428.2 1434.27     438  1437.4   477.1 1449.17
   506.4 1458.39   516.2  1461.2   545.6 1468.66   555.4 1470.77   565.2  1472.2
#Mann= 3 , 0 , 0
       0      .1       0   275.4    .045       0   295.4      .1       0
Bank Sta=275.4,295.4
XS Rating Curve= 0 ,0
Exp/Cntr=0.3,0.1

Type RM Length L Ch R = 1 ,2812    ,345.5,343.8,341.9
XS GIS Cut Line= 4
     1879573.593      347739.434     1879465.086      347806.708
     1879311.006      347858.792     1879115.693       347986.83
#Sta/Elev= 30
       0 1424.87    68.8 1416.72    98.2 1412.96     108 1411.41   117.8 1409.48
   127.7 1407.17   137.2  1404.7   146.8 1401.93   156.4 1398.63   165.9 1395.65
   175.5 1394.13   185.1 1393.96   204.2 1394.14   213.8 1393.04   223.3 1390.35
   242.5 1382.75   249.8 1380.95     252 1380.41   261.6 1381.24   269.8 1384.78
   271.2 1385.39   280.8  1390.7   290.3 1394.88     300 1398.07   368.2 1419.41
   397.4 1428.87   436.3 1442.05   504.4 1465.75   514.1 1469.03   523.8 1471.81
#Mann= 3 , 0 , 0
       0      .1       0   249.8    .045       0   269.8      .1       0
Bank Sta=249.8,269.8
XS Rating Curve= 0 ,0
Exp/Cntr=0.3,0.1

Type RM Length L Ch R = 1 ,2468.2  ,208.3,214.2,219.6
XS GIS Cut Line= 4
     1879703.801      347459.486     1879365.259      347474.677
      1879226.37      347533.271     1879076.631      347663.479
#Sta/Elev= 30
       0 1434.67    48.4 1425.63    58.1 1422.96    67.8 1419.62    96.8 1408.49
   106.5 1405.44   116.2 1403.48   125.9 1402.78   154.9 1402.58   174.3 1401.07
   203.3 1395.84   271.1 1381.18   300.2  1375.8   309.8 1374.53   357.7 1371.64
   414.2 1369.44   423.7 1368.45   436.3 1366.15   442.5 1365.09   451.9 1364.73
   456.3    1366   461.4 1367.48   470.8 1373.95   480.2 1381.18   499.1  1392.5
   527.4 1408.23   546.3 1417.01   621.9 1440.75   659.7 1448.71   688.1 1455.81
#Mann= 3 , 0 , 0
       0      .1       0   436.3    .045       0   456.3      .1       0
Bank Sta=436.3,456.3
XS Rating Curve= 0 ,0
Exp/Cntr=0.3,0.1

Type RM Length L Ch R = 1 ,2253.9  ,96.4,94.6,92.1
XS GIS Cut Line= 4
      1879688.61      347257.663     1879181.232      347340.129
     1879093.992       347357.49     1878889.999      347439.955
#Sta/Elev= 30
       0 1408.42    67.9 1392.08    87.3 1388.55      97  1387.4   145.5  1385.3
   203.7 1379.78   232.8  1377.7     291 1372.03   300.7 1371.48   329.8  1371.2
   407.4 1371.49   426.8 1370.57   484.9 1365.82   522.9 1364.96   531.8 1363.49
   550.6 1357.39   558.5 1356.21   567.4  1357.1   570.6 1358.17   585.2 1363.76
   594.1  1366.6   612.6 1369.83   622.1 1372.12     670 1387.13   679.5 1389.54
   717.8  1397.7   736.9 1400.73   765.6 1403.47   794.3 1405.43     823 1406.72
#Mann= 3 , 0 , 0
       0      .1       0   550.6    .045       0   570.6      .1       0
Bank Sta=550.6,570.6
XS Rating Curve= 0 ,0
Exp/Cntr=0.3,0.1

Type RM Length L Ch R = 1 ,2159.4  ,113.6,110,107.1
XS GIS Cut Line= 5
     1879686.686       347201.97     1879235.297      347238.429
     1879120.714      347260.998     1879046.061      347281.831
     1878832.519      347410.304
#Sta/Elev= 30
       0 1401.57    28.9 1394.44    48.2 1391.04    67.4 1389.14    96.4 1388.69
   115.6 1387.54   154.2 1383.25   192.7 1375.87   260.2 1369.02   289.1 1367.66
   327.6 1369.38   404.7 1369.83     424 1369.38   452.9 1366.95     521  1358.4
   530.7 1357.78   579.3 1357.59   601.1 1354.84   608.4 1354.31   618.1    1356
   621.1 1357.41   637.5 1364.76   666.3 1371.53   685.5  1373.2   723.8 1374.97
     743 1377.37   781.3 1387.89   800.5  1390.9   877.2 1398.73   896.4 1399.39
#Mann= 3 , 0 , 0
       0      .1       0   601.1    .045       0   621.1      .1       0
#XS Ineff= 2 , 0
          573.46 1358.71
Permanent Ineff=
       F       F
Bank Sta=601.1,621.1
XS Rating Curve= 0 ,0
Exp/Cntr=0.3,0.1