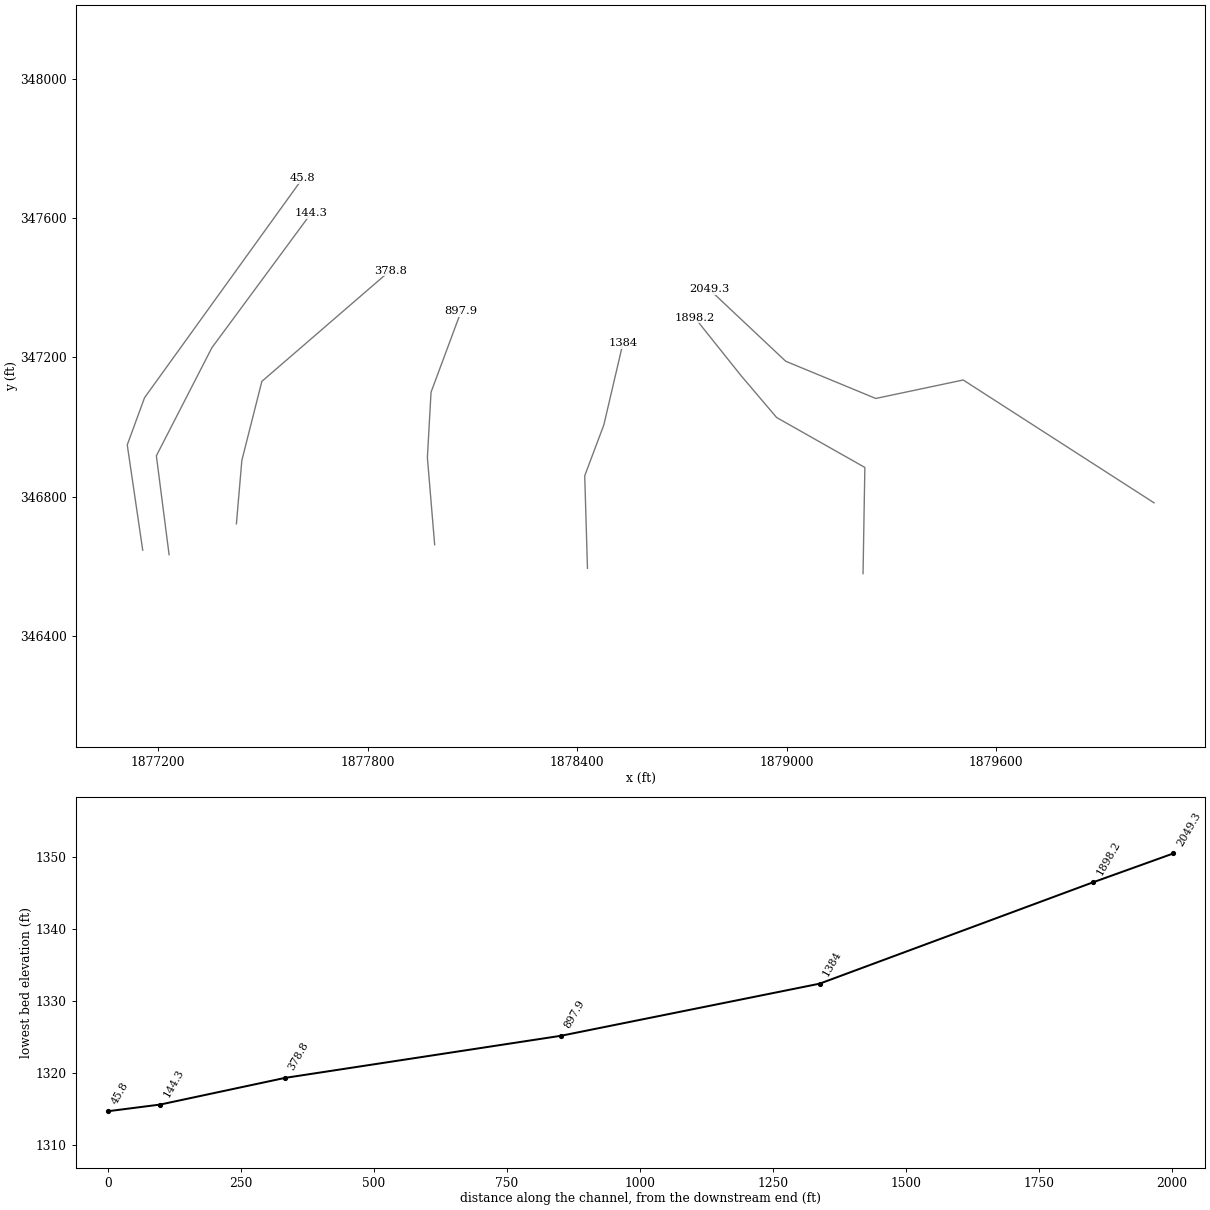
HEC-RAS study THREEFRKCK.prj: THREEFRKCK

--- THREEFRKCK.g01 (geometry) --- (continued)

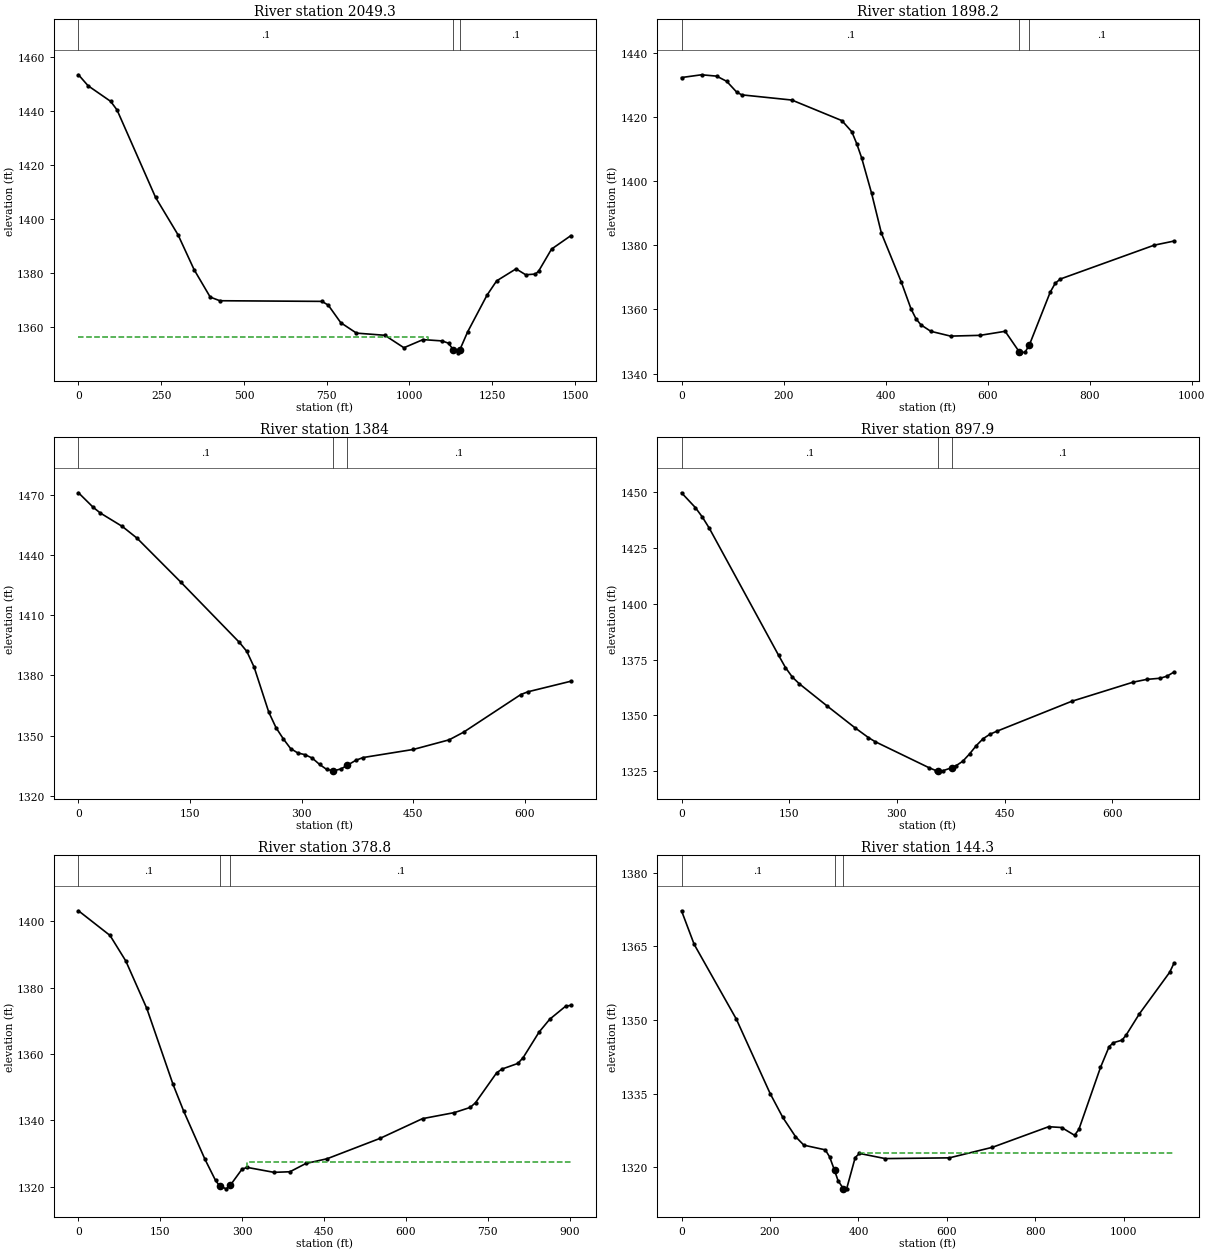
Type RM Length L Ch R = 1 ,2049.3  ,163.2,151.1,139.5
XS GIS Cut Line= 5
     1880051.891      346782.837     1879505.374      347135.315
     1879255.016      347082.316     1878997.204      347189.087
     1878777.152      347396.552
#Sta/Elev= 30
       0 1453.42    29.1 1449.35    97.1 1443.59   116.5  1440.4     233    1408
   300.9 1394.14   349.4 1381.26     398 1371.12   427.1 1369.77   735.6 1369.53
   754.6 1368.14   792.5 1361.63   839.9 1357.78   925.5 1356.98   983.2 1352.37
  1040.9 1355.38  1098.7 1354.89  1117.9 1354.04  1131.9 1351.69  1146.8 1350.48
  1151.9 1351.53  1175.7 1358.24  1234.1  1371.8  1263.3 1377.12  1321.9 1381.57
  1351.1 1379.39  1380.4 1379.64  1390.2 1380.73  1429.2 1388.89  1487.7 1393.88
#Mann= 3 , 0 , 0
       0      .1       0  1131.9    .045       0  1151.9      .1       0
#XS Ineff= 2 , 0
         1056.08 1356.18
Permanent Ineff=
       F       F
Bank Sta=1131.9,1151.9
XS Rating Curve= 0 ,0
Exp/Cntr=0.3,0.1

Type RM Length L Ch R = 1 ,1898.2  ,541.1,514.3,487
XS GIS Cut Line= 5
     1879218.558      346579.712     1879223.766      346884.399
     1878971.162      347027.629       1878869.6       347147.42
     1878736.787      347314.087
#Sta/Elev= 30
       0 1432.21    39.3 1433.07    68.8 1432.65    88.5 1431.04   108.1 1427.68
     118 1426.82   216.3  1425.2   314.4 1418.79   333.8 1415.33   343.4 1411.63
   353.1 1407.19   372.5 1396.22   391.8 1383.75   430.6 1368.62   449.9 1360.16
   459.6 1357.09   469.3 1355.19   488.6 1353.18   527.4 1351.68   585.4 1351.92
   634.4 1353.18   662.1 1346.77   663.8 1346.47   673.6 1346.69   682.1 1349.02
   722.7 1365.35   732.5 1368.12   742.4 1369.45   926.5    1380   965.3 1381.28
#Mann= 3 , 0 , 0
       0      .1       0   662.1    .045       0   682.1      .1       0
Bank Sta=662.1,682.1
XS Rating Curve= 0 ,0
Exp/Cntr=0.3,0.1

Type RM Length L Ch R = 1 ,1384    ,478.3,486.1,493.6
XS GIS Cut Line= 4
     1878429.495      346594.903     1878421.683      346860.528
      1878476.37      347006.361     1878531.058      347240.736
#Sta/Elev= 30
       0 1470.98    19.7 1463.78    29.5 1460.86      59 1454.19    78.7 1448.37
   137.8 1426.38   216.5 1396.37   226.4 1391.91   236.2 1384.08   255.9 1361.64
   265.7 1353.86   275.5 1348.31   285.2 1343.52   294.9  1341.3   304.7 1340.44
   314.4 1338.74   324.2 1335.59   333.9 1333.06   341.7 1332.52   343.6 1332.39
   353.4 1333.42   361.7  1335.2   372.8  1337.6   382.6 1339.01   450.4 1343.06
   498.5 1347.85   517.8 1351.64   594.8 1370.41   604.4 1371.79   662.2 1377.06
#Mann= 3 , 0 , 0
       0      .1       0   341.7    .045       0   361.7      .1       0
Bank Sta=341.7,361.7
XS Rating Curve= 0 ,0
Exp/Cntr=0.3,0.1

Type RM Length L Ch R = 1 ,897.9   ,524,519,514
XS GIS Cut Line= 4
     1877991.995      346662.611     1877971.162      346912.611
     1877981.579      347100.111     1878067.516      347331.882
#Sta/Elev= 30
       0 1449.72    19.3 1443.08      29 1438.86    38.6 1433.89   135.1 1376.97
   144.7 1371.45   154.4 1367.13     164 1364.17   202.6 1354.26   241.2 1344.54
   260.3 1340.06   269.6 1338.24   344.8 1326.54   354.2  1325.3   356.7 1325.26
   363.5 1325.16   376.7  1326.6   382.3 1327.45   391.7 1329.46   401.1 1332.72
   410.5 1336.46   419.9 1339.52   429.3 1341.51   438.7 1342.84   543.2 1356.29
   628.8 1364.87   647.8 1366.12   666.8 1366.65   676.3 1367.59   685.8 1369.41
#Mann= 3 , 0 , 0
       0      .1       0   356.7    .045       0   376.7      .1       0
Bank Sta=356.7,376.7
XS Rating Curve= 0 ,0
Exp/Cntr=0.3,0.1

Type RM Length L Ch R = 1 ,378.8   ,240.2,234.6,228.5
XS GIS Cut Line= 4
     1877424.287      346722.507     1877439.912      346904.799
     1877497.204      347131.361     1877864.391       347449.07
#Sta/Elev= 30
       0 1403.13    57.8 1395.69    86.7    1388   125.2 1373.69   173.3 1350.77
   192.7 1342.75   231.6 1328.27   251.1 1321.85   258.5 1320.23   270.6 1319.31
   278.5 1320.47   299.8 1325.28   309.5 1325.76   358.2 1324.28   387.4 1324.46
   416.6 1326.95   455.5 1328.38   552.6 1334.53   630.3 1340.47   688.6 1342.29
   717.7 1343.85   727.4 1345.27   766.2  1354.3     776 1355.42   805.1 1357.12
   814.8 1358.89   843.9 1366.57   863.4 1370.44   892.5 1374.36   902.2 1374.62
#Mann= 3 , 0 , 0
       0      .1       0   258.5    .045       0   278.5      .1       0
#XS Ineff= 2 , 0
                          308.04         1327.34
Permanent Ineff=
       F       F
Bank Sta=258.5,278.5
XS Rating Curve= 0 ,0
Exp/Cntr=0.3,0.1

Type RM Length L Ch R = 1 ,144.3   ,95.1,98.5,101.9
XS GIS Cut Line= 4
     1877231.579      346633.965      1877195.12       346917.82
     1877353.975      347227.715     1877637.829      347613.132
#Sta/Elev= 30
       0 1372.23    28.6 1365.39     124 1350.15   200.3 1335.02     229 1330.14
   257.6 1326.25   276.6  1324.5   324.9 1323.55   334.6 1322.15   345.9 1319.37
   353.9 1317.25   365.9 1315.66   373.2 1315.61   392.6 1321.99   402.3 1322.82
   460.3 1321.77   605.4 1321.92   702.8 1324.07   829.8 1328.26   859.1  1328.1
   888.4 1326.52   898.2 1327.72     947 1340.32   966.6 1344.57   976.3 1345.37
   995.9 1345.89  1005.6 1347.01  1034.9 1351.24  1103.3 1359.69  1113.1 1361.54
#Mann= 3 , 0 , 0
       0      .1       0   345.9    .045       0   365.9      .1       0
#XS Ineff= 2 , 0
                          402.25         1322.94
Permanent Ineff=
       F       F
Bank Sta=345.9,365.9
XS Rating Curve= 0 ,0
Exp/Cntr=0.3,0.1

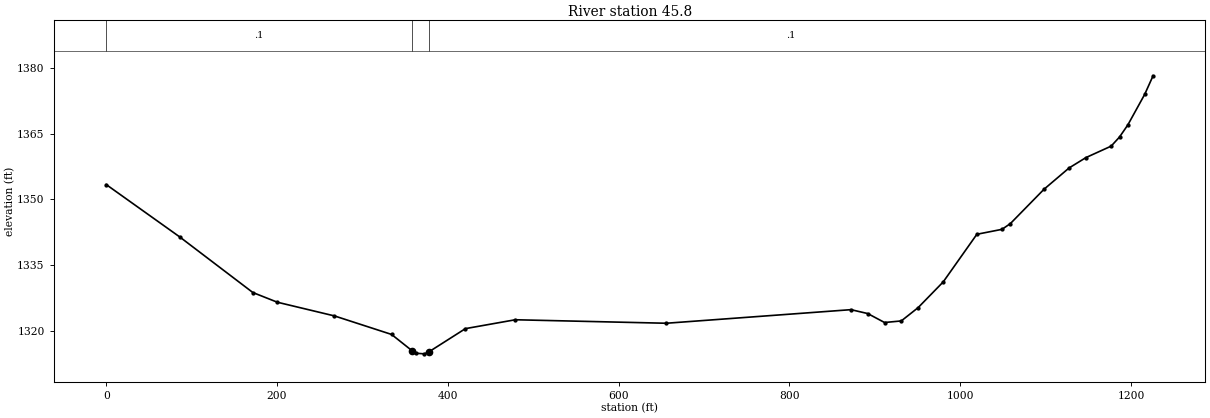
Type RM Length L Ch R = 1 ,45.8    ,42.1,45.8,49.5
XS GIS Cut Line= 4
     1877156.058      346646.986     1877111.787       346949.07
     1877161.266      347084.486     1877614.391      347714.695
#Sta/Elev= 30
       0 1353.42    85.9 1341.46   171.7 1328.71   200.4 1326.49   267.2 1323.36
   334.1 1319.12   357.8 1315.44     363 1314.81   372.6 1314.68   377.8 1315.13
   420.6 1320.45     479 1322.48   655.8 1321.68     872 1324.79   891.6  1323.9
   911.3 1321.85   930.9 1322.21   950.6 1325.25     980 1331.14  1019.4 1342.04
  1048.8 1343.17  1058.6 1344.48    1098 1352.34  1127.4 1357.22  1147.1 1359.59
  1176.6 1362.21  1186.4 1364.29  1196.2 1367.08  1215.9 1374.06  1225.7 1378.31
#Mann= 3 , 0 , 0
       0      .1       0   357.8    .045       0   377.8      .1       0
Bank Sta=357.8,377.8
XS Rating Curve= 0 ,0
Exp/Cntr=0.3,0.1

Chan Stop Cuts=-1
Use User Specified Reach Order=0
Composite Channel Slope=5